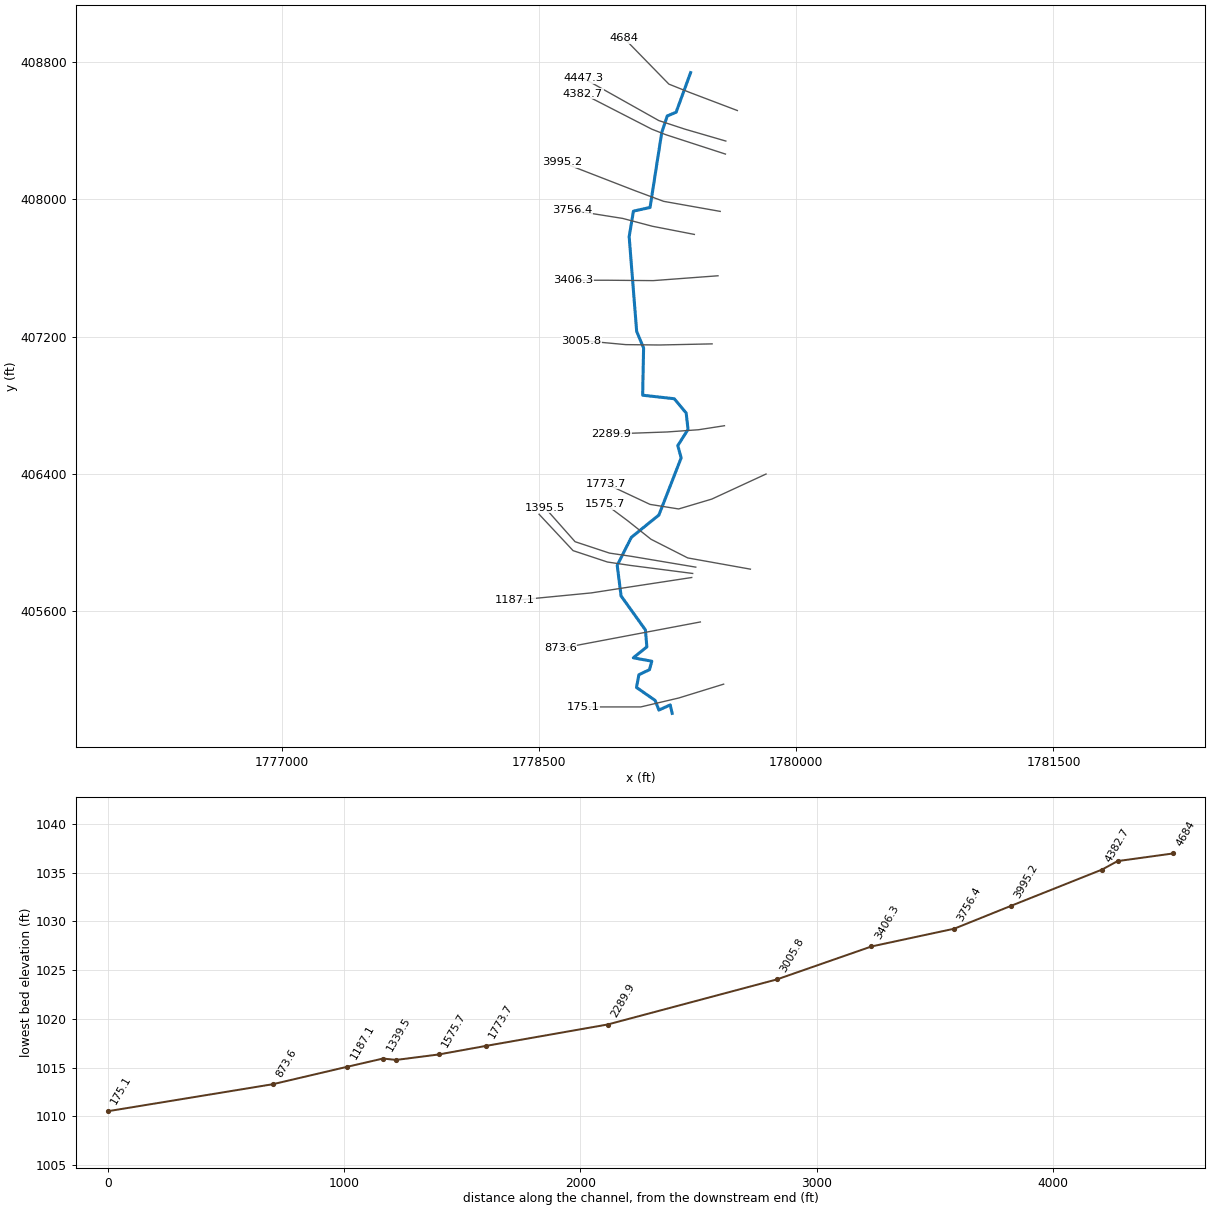
--- LPawpawCk.prj (project) ---

Proj Title=LPawpawCk
Current Plan=p01
Default Exp/Contr=0,0
English Units
Geom File=g01
Flow File=f01
Plan File=p01
BEGIN DESCRIPTION:
END DESCRIPTION:
DSS Export Rating Curves= 0
DSS Export Rating Curve Sorted= 0
DSS Export Volume Flow Curves= 0
DXF OffsetX= 0
DXF OffsetY= 0
DXF ScaleX= 0
DXF ScaleY= 0

--- LPawpawCk.p01 (plan) ---

Plan Title=Floodplain
Program Version=4.00
Geom File=g01
Flow File=f01
K Sum by GR=0
Std Step Tol=0.01
Critical Tol=0.01
Num of Std Step Trials=20
Max Error Tol=0.3
Flow Tol Ratio=0.001
Split Flow NTrial=30
Split Flow Tol=0.02
Split Flow Ratio=0.02
Log Output Level=0
Friction Slope Method=1
Unsteady Friction Slope Method=2
Unsteady Bridges Friction Slope Method=1
Global Log Level=0
CheckData=False
Run HTab=0
Run UNet=0
Run PostProcess=0
UNET Theta=0
UNET Theta Warmup=0
UNET ZTol=0
UNET ZSATol=0
UNET MxIter=0
UNET MaxInSteps=0
UNET DtIC=0
UNET DtMin=0
UNET MaxCRTS=0
UNET WFStab=0
UNET SFStab=0
UNET WFX=0
UNET SFX=0
UNET DSS MLevel=0
UNET DZMax Abort=0
UNET Convert EG Bridges=0
UNET Use Existing IB Tables=0
UNET Froude Limit=0
UNET Froude Power=0
Write IC File=0
Echo Input=False
Echo Output=False
Write Detailed=0

--- LPawpawCk.f01 (steady flow) ---

Flow Title=NFF Regression Equation
Program Version=4.10
Number of Profiles= 1
Profile Names=P100yr
River Rch & RM=LPawpawCk,Main            ,4684
     518
River Rch & RM=LPawpawCk,Main            ,3995.2
     694
River Rch & RM=LPawpawCk,Main            ,1773.7
     736
River Rch & RM=LPawpawCk,Main            ,1395.5
     901
River Rch & RM=LPawpawCk,Main            ,1187.1
    1105
River Rch & RM=LPawpawCk,Main            ,175.1
    1112
Boundary for River Rch & Prof#=LPawpawCk,Main            , 1
Up Type= 0
Dn Type= 3
Dn Slope=0.0056
DSS Import GetInterval= 0
DSS Import GetPeak= 0
DSS Import FillOption= 0

--- LPawpawCk.g01 (geometry) ---

Geom Title=USGS 10m DEM
Program Version=4.10

River Reach=LPawpawCk       ,Main
Reach XY= 30
     1779384.179      408738.786      1779299.67      408507.963
     1779247.847      408486.088     1779215.746      408389.068
     1779147.725      407952.548     1779050.943      407931.285
     1779025.881      407782.121     1779069.652      407229.556
     1779110.008      407133.322     1779104.575      406857.815
     1779288.986      406837.205     1779358.352      406753.821
     1779369.217      406658.364     1779309.309      406563.815
     1779329.147      406492.616     1779199.256      406159.192
     1779038.368      406028.678     1778956.261       405865.46
     1778978.691       405687.21     1779120.772      405488.985
     1779128.897      405390.331     1779049.974      405326.496
     1779157.913      405306.765     1779144.368      405257.433
     1779082.472      405227.843     1779068.695      405153.616
      1779177.41       405078.07     1779199.333      405021.731
     1779265.273       405051.76     1779276.697      405002.518

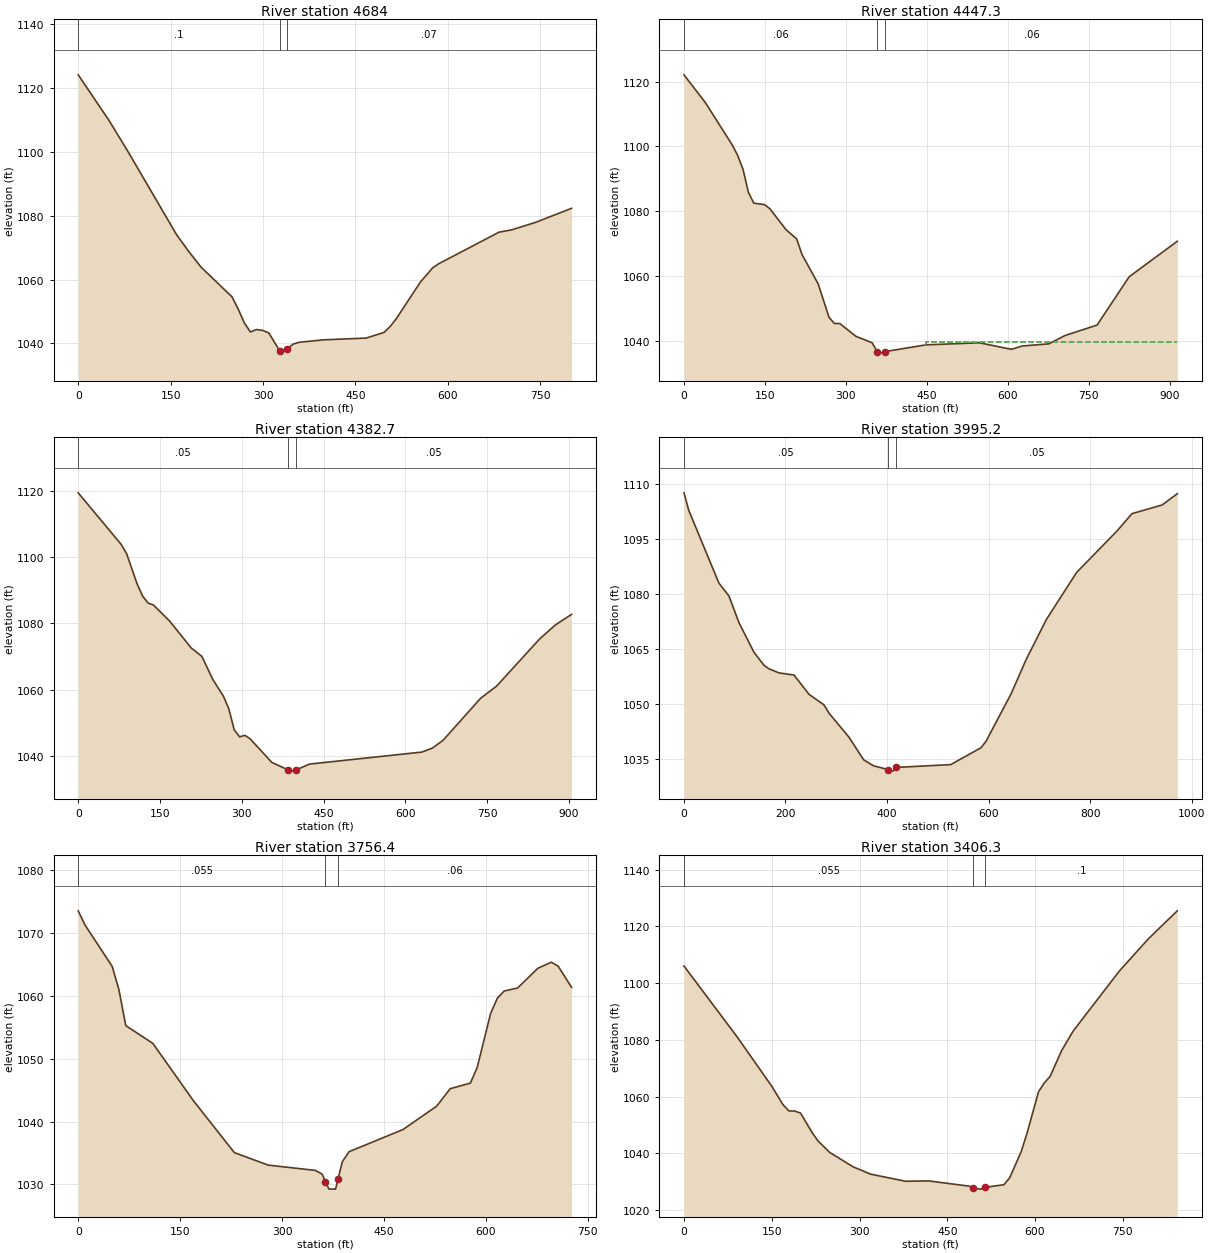
Type RM Length L Ch R = 1 ,4684    ,234.3,236.7,237.5
XS GIS Cut Line= 4
     1779656.731        408517.8     1779376.783      408624.137
     1779257.425       408671.88     1778997.009      408938.807
#Sta/Elev= 30
       0 1124.15    49.9 1109.89    79.9 1100.41   159.7 1074.06   179.7 1068.74
   199.6 1063.87   249.6 1054.61   259.5 1050.87   269.5  1046.5   279.5 1043.59
   289.5 1044.35   299.5 1044.08   309.4 1043.29   326.8 1037.77   329.1 1036.96
     339 1038.11   348.9  1039.8   358.8 1040.36   398.4 1041.13   467.3 1041.67
   496.7 1043.46   506.5 1045.33   516.3 1047.72   555.6 1059.25   575.2 1063.63
     585 1064.94   683.2 1074.86   702.8 1075.53     742  1077.9   800.9 1082.32
#Mann= 3 , 0 , 0
       0      .1       0   326.8    .045       0     339     .07       0
Bank Sta=326.8,339
XS Rating Curve= 0 ,0
Exp/Cntr=0.3,0.1

Type RM Length L Ch R = 1 ,4447.3  ,65.7,64.6,63.1
XS GIS Cut Line= 4
     1779589.457      408339.849     1779350.741      408409.293
     1779198.832      408459.206     1778758.294      408706.602
#Sta/Elev= 30
       0 1122.13    39.8 1113.52    89.5 1100.45    99.4 1097.28   109.4 1092.94
   119.3  1085.9   129.3  1082.5   149.2 1082.04   159.1 1080.79   188.9 1074.33
   208.8 1071.43   218.8 1066.59   248.6 1057.56   268.6 1047.28   278.6 1045.33
   288.6 1045.31   318.6 1041.35   348.6 1039.38   358.2 1036.51   368.5 1036.17
   373.2 1036.67   448.1 1038.72   547.2 1039.36   606.6 1037.35   626.5 1038.37
     676 1039.04   705.7  1041.6   765.2 1044.84   824.6 1059.75   913.8 1070.72
#Mann= 3 , 0 , 0
       0     .06       0   358.2    .045       0   373.2     .06       0
#XS Ineff= 2 , 0
                          447.72         1039.47
Permanent Ineff=
       F       F
Bank Sta=358.2,373.2
XS Rating Curve= 0 ,0
Exp/Cntr=0.3,0.1

Type RM Length L Ch R = 1 ,4382.7  ,386.2,387.4,386.8
XS GIS Cut Line= 4
     1779587.287      408263.894     1779240.064      408376.741
     1779157.599      408409.293     1778756.123      408615.456
#Sta/Elev= 30
       0 1119.54    78.9 1103.92    88.8 1101.12   108.5 1091.78   118.4 1088.23
   128.3 1086.16   138.2 1085.57   167.8 1080.71   207.2 1072.61     227 1070.01
   246.7 1063.11   266.4    1058   276.3 1054.17   286.2 1047.83     296  1045.7
   305.9 1046.14   315.8 1045.02   355.2 1037.95   384.4 1035.73   394.6 1035.31
   399.4 1035.65   424.2 1037.44   630.4 1041.07     650  1042.3   669.6 1044.68
   738.3 1057.37   767.7 1061.06   846.2 1075.26   875.6 1079.59   905.1 1082.76
#Mann= 3 , 0 , 0
       0     .05       0   384.4    .045       0   399.4     .05       0
Bank Sta=384.4,399.4
XS Rating Curve= 0 ,0
Exp/Cntr=0.3,0.1

Type RM Length L Ch R = 1 ,3995.2  ,235.1,238.9,240.5
XS GIS Cut Line= 4
     1779556.905      407929.692     1779227.044      407988.286
     1779057.773       408051.22     1778632.425      408216.151
#Sta/Elev= 30
       0 1107.66     9.8 1102.76      69 1082.94    88.7 1079.44   108.4 1072.15
     138 1064.05   157.7  1060.5   167.5 1059.54   187.2 1058.43   216.8 1057.84
   246.3 1052.58   275.9 1049.67   285.8  1047.4   325.2 1040.82     354 1034.66
     373 1033.05   401.6 1032.01   411.1 1031.57     418 1032.58   525.5 1033.35
     585 1037.96     595 1039.73   644.5 1052.73   674.3 1062.15     714 1073.05
   773.5  1085.9   852.8  1097.2   882.6 1101.97   942.1 1104.35   971.8 1107.43
#Mann= 3 , 0 , 0
       0     .05       0   401.6    .045       0     418     .05       0
Bank Sta=401.6,418
XS Rating Curve= 0 ,0
Exp/Cntr=0.3,0.1

Type RM Length L Ch R = 1 ,3756.4  ,344.6,350.1,355.7
XS GIS Cut Line= 4
     1779406.028      407795.369     1779160.803      407843.113
     1778988.277      407888.685     1778694.223      407935.343
#Sta/Elev= 30
       0 1073.52      10 1071.27      50 1064.68      60 1060.94      70 1055.26
   109.9 1052.42   169.9 1043.25   229.8 1035.05   279.6 1033.06     349 1032.22
   358.9 1031.64  363.89 1030.45   368.8 1029.26   378.7 1029.24   382.2 1030.78
   388.6 1033.59   398.5 1035.19   477.9 1038.72   527.5 1042.44   547.4 1045.22
   577.1 1046.11   587.1 1048.58   606.9  1057.2   616.8 1059.62   626.8 1060.76
   646.6 1061.24   676.4 1064.38   696.2 1065.34   706.2 1064.72     726 1061.35
#Mann= 3 , 0 , 0
       0    .055       0  363.89    .045       0   382.2     .06       0
Bank Sta=363.89,382.2
XS Rating Curve= 0 ,0
Exp/Cntr=0.3,0.1

Type RM Length L Ch R = 1 ,3406.3  ,401,400.5,403
XS GIS Cut Line= 4
     1779543.884      407554.258      1779166.28      407526.046
     1778899.353      407528.217      1778701.87      407528.217
#Sta/Elev= 30
       0 1106.06    89.7  1081.4   149.5 1063.85   169.4 1057.14   179.4 1054.96
   189.3 1054.94   199.3  1054.2   219.2  1047.3   229.2 1044.38   249.1 1040.35
     289 1035.28   318.9  1032.7   378.7  1030.2   418.2 1030.31   487.4 1028.47
  494.52 1027.82   507.2 1027.42   515.3 1028.09   546.7 1028.96   556.6 1031.37
   576.4 1040.67   586.3 1047.11     606 1061.77   615.9 1064.86   625.8 1067.16
   645.6 1076.32   665.3 1083.17   744.3 1104.33   793.7 1115.62   843.1 1125.48
#Mann= 3 , 0 , 0
       0    .055       0  494.52    .045       0   515.3      .1       0
Bank Sta=494.52,515.3
XS Rating Curve= 0 ,0
Exp/Cntr=0.3,0.1

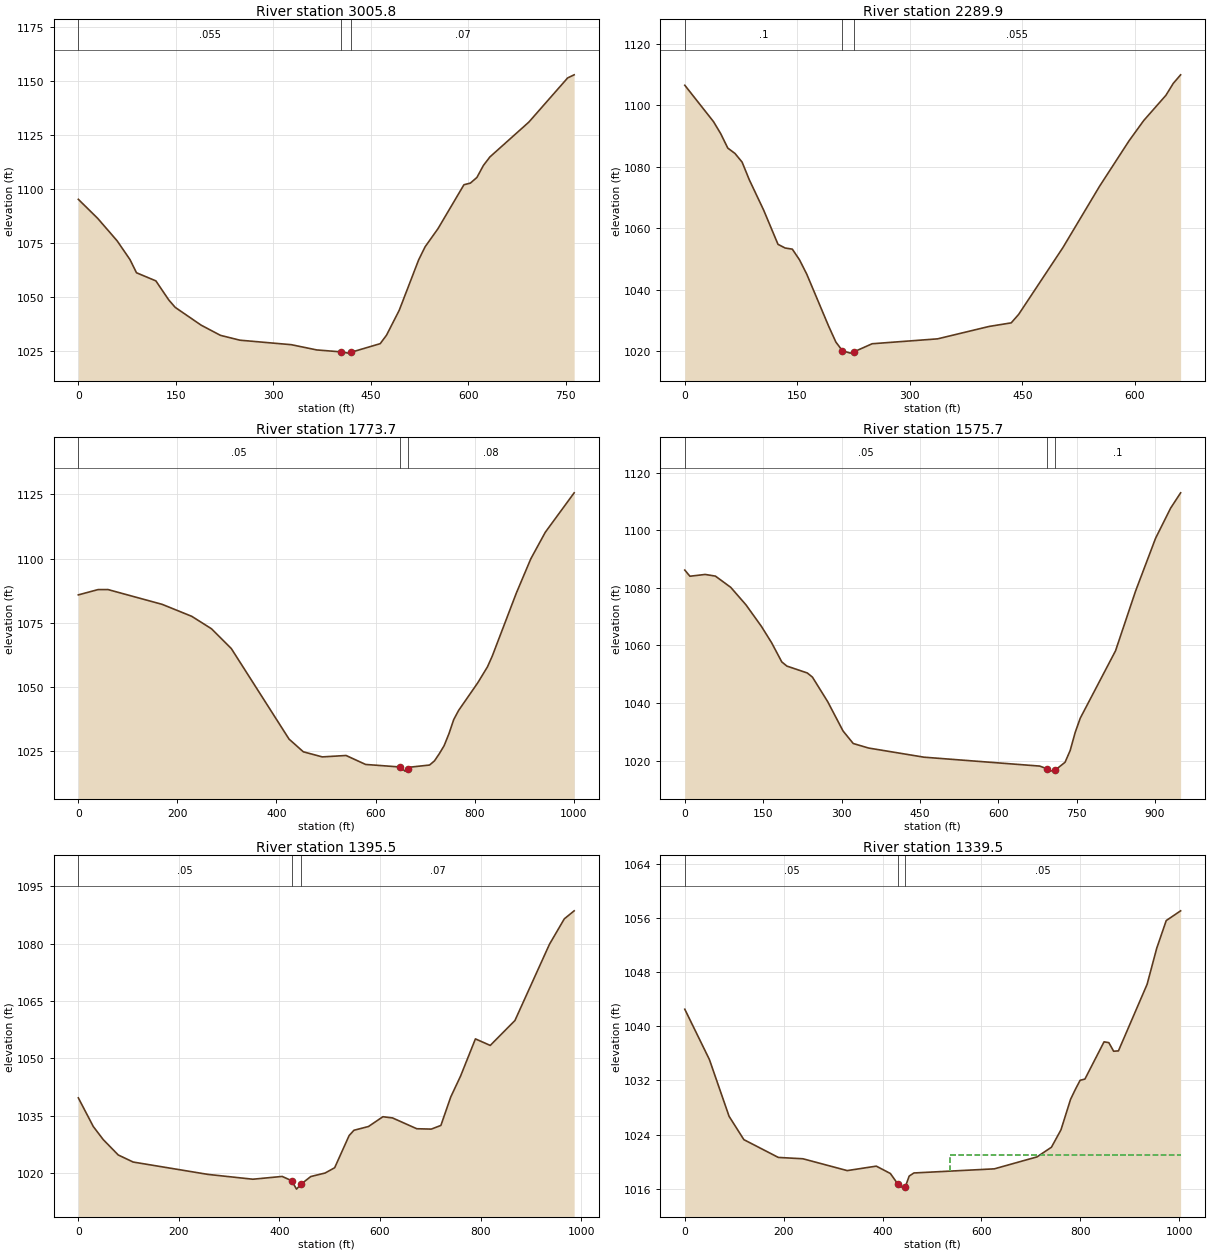
Type RM Length L Ch R = 1 ,3005.8  ,710.9,715.9,715.9
XS GIS Cut Line= 4
     1779509.596      407157.123     1779201.436      407150.612
     1779006.123      407152.783     1778747.877      407176.654
#Sta/Elev= 30
       0 1095.26    29.8 1086.44    59.7 1076.04    79.5 1067.35    89.5 1061.25
   119.3  1057.5   139.2 1048.65   149.1 1045.22   188.9    1037   218.7 1032.27
   248.6 1030.03   327.8 1027.94   366.8 1025.52   404.7 1024.61   415.7 1024.04
   419.7 1024.44   464.5 1028.43   474.2 1032.35   493.8 1043.91   523.5 1067.13
   533.5 1073.25   553.4 1081.68   593.3    1102   603.3 1102.79   613.3  1105.4
   623.2 1110.91   633.2 1114.87   693.1 1130.99   752.9 1151.48   762.9 1152.91
#Mann= 3 , 0 , 0
       0    .055       0   404.7    .045       0   419.7     .07       0
Bank Sta=404.7,419.7
XS Rating Curve= 0 ,0
Exp/Cntr=0.3,0.1

Type RM Length L Ch R = 1 ,2289.9  ,523.3,516.2,523.2
XS GIS Cut Line= 4
      1779581.54      406679.913     1779430.498      406656.476
     1779246.904      406643.455     1778923.224      406631.949
#Sta/Elev= 30
       0 1106.52    38.2 1094.71    47.8 1090.81    57.3 1086.09    66.9 1084.34
    76.4 1081.52      86 1075.76   105.1 1065.92   124.2  1054.8   133.7  1053.6
   143.3 1053.23   152.8 1049.79   162.5 1045.12   191.6 1028.25   201.3 1023.04
     210  1020.2   220.7 1019.42     225 1019.79   249.7 1022.47   336.9 1024.06
   405.6  1028.1     435 1029.26   444.9    1032   503.8 1053.69   552.8 1073.69
   592.1 1088.47   611.7 1095.07   641.2 1103.25     651 1107.13   660.8 1109.91
#Mann= 3 , 0 , 0
       0      .1       0     210    .045       0     225    .055       0
Bank Sta=210,225
XS Rating Curve= 0 ,0
Exp/Cntr=0.3,0.1

Type RM Length L Ch R = 1 ,1773.7  ,211.2,198,185
XS GIS Cut Line= 5
     1779824.002      406398.179     1779507.523       406252.02
     1779314.381      406194.511     1779147.659      406221.141
     1778892.451      406340.933
#Sta/Elev= 30
       0 1085.86    39.8 1087.92    59.8 1087.94   169.3 1082.17   229.1  1077.5
   268.9 1072.65   308.8 1064.96   425.4 1029.69   454.2 1024.74   492.5 1022.76
   540.5 1023.31   579.9 1019.82   649.8 1018.83   659.4 1017.22   664.8 1018.06
   669.3 1018.76     709 1019.59     719 1021.23   728.7 1024.01   738.4 1027.13
   748.1 1031.77   757.8  1037.3   767.6 1040.84   806.4 1051.65   825.9 1057.84
   835.6 1062.03   884.2 1086.58   913.4 1099.91   942.6 1110.24  1000.9 1125.61
#Mann= 3 , 0 , 0
       0     .05       0   649.8    .045       0   664.8     .08       0
Bank Sta=649.8,664.8
XS Rating Curve= 0 ,0
Exp/Cntr=0.3,0.1

Type RM Length L Ch R = 1 ,1575.7  ,168.1,180.2,192.3
XS GIS Cut Line= 5
     1779732.856      405843.491     1779367.399      405908.954
     1779153.259        406017.8      1779016.54      406126.307
      1778885.94      406223.745
#Sta/Elev= 30
       0 1086.16     9.8 1084.02    39.1 1084.64    58.6 1084.06    87.9 1080.17
   117.2 1074.06   146.6 1066.62   166.1 1060.95   185.6 1054.28   195.4 1052.82
   234.5 1050.43   244.3 1048.99   273.6 1040.44   302.9 1030.29   322.4 1025.94
   351.7 1024.37   457.8 1021.19   679.4  1018.1   693.6 1017.13   698.8 1016.35
   708.6 1016.65   727.8 1019.43   737.6 1023.51   747.2 1029.78   756.9 1034.74
   824.4 1058.12   862.7 1078.83     901 1097.17   929.8 1107.65     949 1112.98
#Mann= 3 , 0 , 0
       0     .05       0   693.6    .045       0   708.6      .1       0
Bank Sta=693.6,708.6
XS Rating Curve= 0 ,0
Exp/Cntr=0.3,0.1

Type RM Length L Ch R = 1 ,1395.5  ,56,56,56
XS GIS Cut Line= 5
     1779414.332       405855.21     1779042.564      405917.612
     1778911.053      405937.143     1778710.532      406003.549
     1778534.653      406202.004
#Sta/Elev= 30
       0 1039.65    29.8 1032.15    49.6 1028.73    79.4 1024.72   109.1 1022.87
   257.9 1019.64   347.2 1018.38   405.5 1019.11   424.4 1017.99     434 1015.79
   443.4 1017.13   462.4 1019.08   490.9    1020   509.9 1021.38   538.7  1029.8
   548.3 1031.18   577.1 1032.16   605.9 1034.72   625.1  1034.4   673.2 1031.58
     702 1031.48   721.2 1032.44   740.8 1039.88   760.4 1045.36   789.9 1055.07
   819.4 1053.36   868.5 1059.88   937.2 1079.81   966.7 1086.45   986.3 1088.55
#Mann= 3 , 0 , 0
       0     .05       0   424.4    .045       0   443.4     .07       0
Bank Sta=424.4,443.4
XS Rating Curve= 0 ,0
Exp/Cntr=0.3,0.1

Type RM Length L Ch R = 1 ,1339.5  ,145.3,152.3,159.2
XS GIS Cut Line= 5
     1779396.276      405818.404     1779030.845      405865.528
     1778899.334       405885.06     1778698.814      405951.466
     1778500.582      406163.593
#Sta/Elev= 30
       0 1042.54    49.8  1035.1    89.6  1026.7   119.5 1023.25   189.2 1020.62
     239 1020.42   328.6 1018.67   387.4 1019.33   415.9 1018.24   431.1 1016.67
   444.4 1015.93   446.1 1016.28   453.9 1017.86   463.4 1018.32   626.2 1018.93
   712.6  1020.7   741.7 1022.13     761 1024.71   780.4 1029.22   790.1 1030.69
   799.7 1032.03   809.4 1032.21   848.1 1037.72   857.8  1037.6   867.5 1036.33
   877.2 1036.38   935.2 1046.23   954.6 1051.55   973.9 1055.66    1003  1057.1
#Mann= 3 , 0 , 0
       0     .05       0   431.1    .045       0   446.1     .05       0
#XS Ineff= 2 , 0
                          535.79            1021
Permanent Ineff=
       F       F
Bank Sta=431.1,446.1
XS Rating Curve= 0 ,0
Exp/Cntr=0.3,0.1

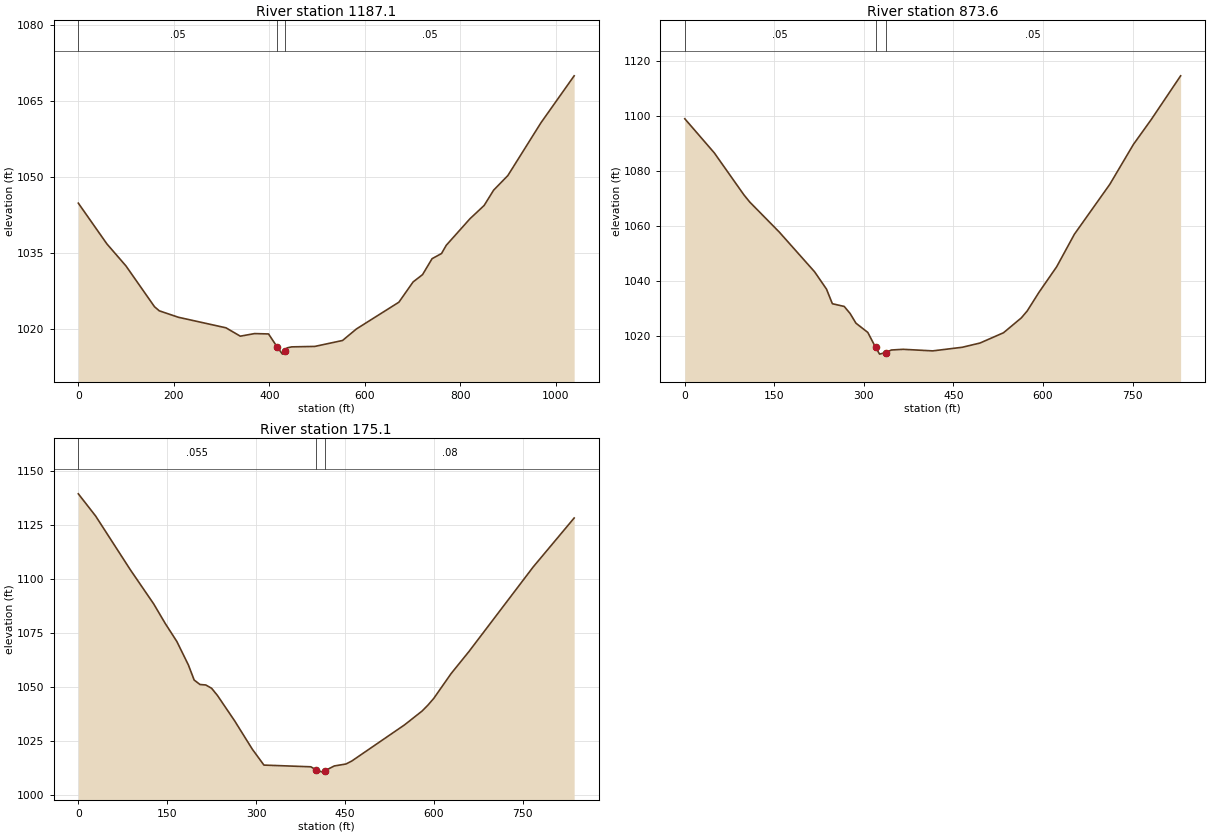
Type RM Length L Ch R = 1 ,1187.1  ,311.7,313.6,314.5
XS GIS Cut Line= 4
     1779390.721      405794.793      1779015.99      405737.594
     1778805.486      405705.042     1778361.158      405661.897
#Sta/Elev= 30
       0 1044.85    59.8 1036.82    99.8 1032.47   159.6 1024.42   169.6 1023.62
   209.5 1022.35   309.2 1020.27   339.2 1018.62   369.1 1019.13   398.4 1019.06
     417 1016.42   427.5 1015.08     432 1015.65   437.2 1016.31   446.8 1016.51
   495.3  1016.6   553.4 1017.77   582.4 1020.04   671.4 1025.32   701.2 1029.32
     721 1030.76   740.9  1033.9   760.7 1034.92   770.6 1036.54   820.2 1041.77
     850  1044.4   869.8 1047.41   899.6 1050.29     969 1060.71  1038.5 1069.96
#Mann= 3 , 0 , 0
       0     .05       0     417    .045       0     432     .05       0
Bank Sta=417,432
XS Rating Curve= 0 ,0
Exp/Cntr=0.3,0.1

Type RM Length L Ch R = 1 ,873.6   ,746.4,698.4,693.3
XS GIS Cut Line= 2
     1779441.013      405535.578     1778624.931      405381.258
#Sta/Elev= 30
       0 1098.87    49.4 1086.47    98.9 1071.24   108.8 1068.59   158.2 1057.69
   217.5 1043.21   237.3 1036.95   247.2 1031.62     267 1030.64   276.8  1028.1
   286.7 1024.54   306.5  1021.2   319.7 1015.71   326.3  1013.3   336.2 1013.87
   346.1  1014.8   365.8 1015.05   415.3 1014.48   464.7 1015.79   494.4 1017.33
   533.9 1021.08   563.6 1026.46   573.5 1028.98   593.2 1035.76   622.9 1045.07
   652.6  1056.9   711.9 1075.04   751.4 1089.53   781.1 1098.53   830.5 1114.48
#Mann= 3 , 0 , 0
       0     .05       0   319.7    .045       0   336.2     .05       0
Bank Sta=319.7,336.2
XS Rating Curve= 0 ,0
Exp/Cntr=0.3,0.1

Type RM Length L Ch R = 1 ,175.1   ,118.8,175.1,163.2
XS GIS Cut Line= 4
     1779576.753      405172.924     1779315.035      405092.195
     1779093.681      405040.112     1778757.743      405040.112
#Sta/Elev= 30
       0 1139.51    29.3 1129.19      88 1104.24   127.2 1088.52   146.7 1079.45
   166.3  1071.1   185.8 1060.22   195.6 1053.21   205.4 1051.14   215.2 1050.92
     225  1049.4   234.8  1046.1   264.1 1034.23   293.7 1021.19   313.4 1013.79
   392.5    1013   402.1  1011.5   412.3 1010.53   417.1 1011.28   432.1 1013.38
   451.8 1014.29   461.7 1015.67   550.7 1032.41   580.3 1038.81   590.2 1041.55
   600.1 1044.69   629.7  1056.3   659.4 1066.36   768.1 1105.64   837.2  1128.3
#Mann= 3 , 0 , 0
       0    .055       0   402.1    .045       0   417.1     .08       0
Bank Sta=402.1,417.1
XS Rating Curve= 0 ,0
Exp/Cntr=0.3,0.1

Chan Stop Cuts=-1
Use User Specified Reach Order=0
Composite Channel Slope=5